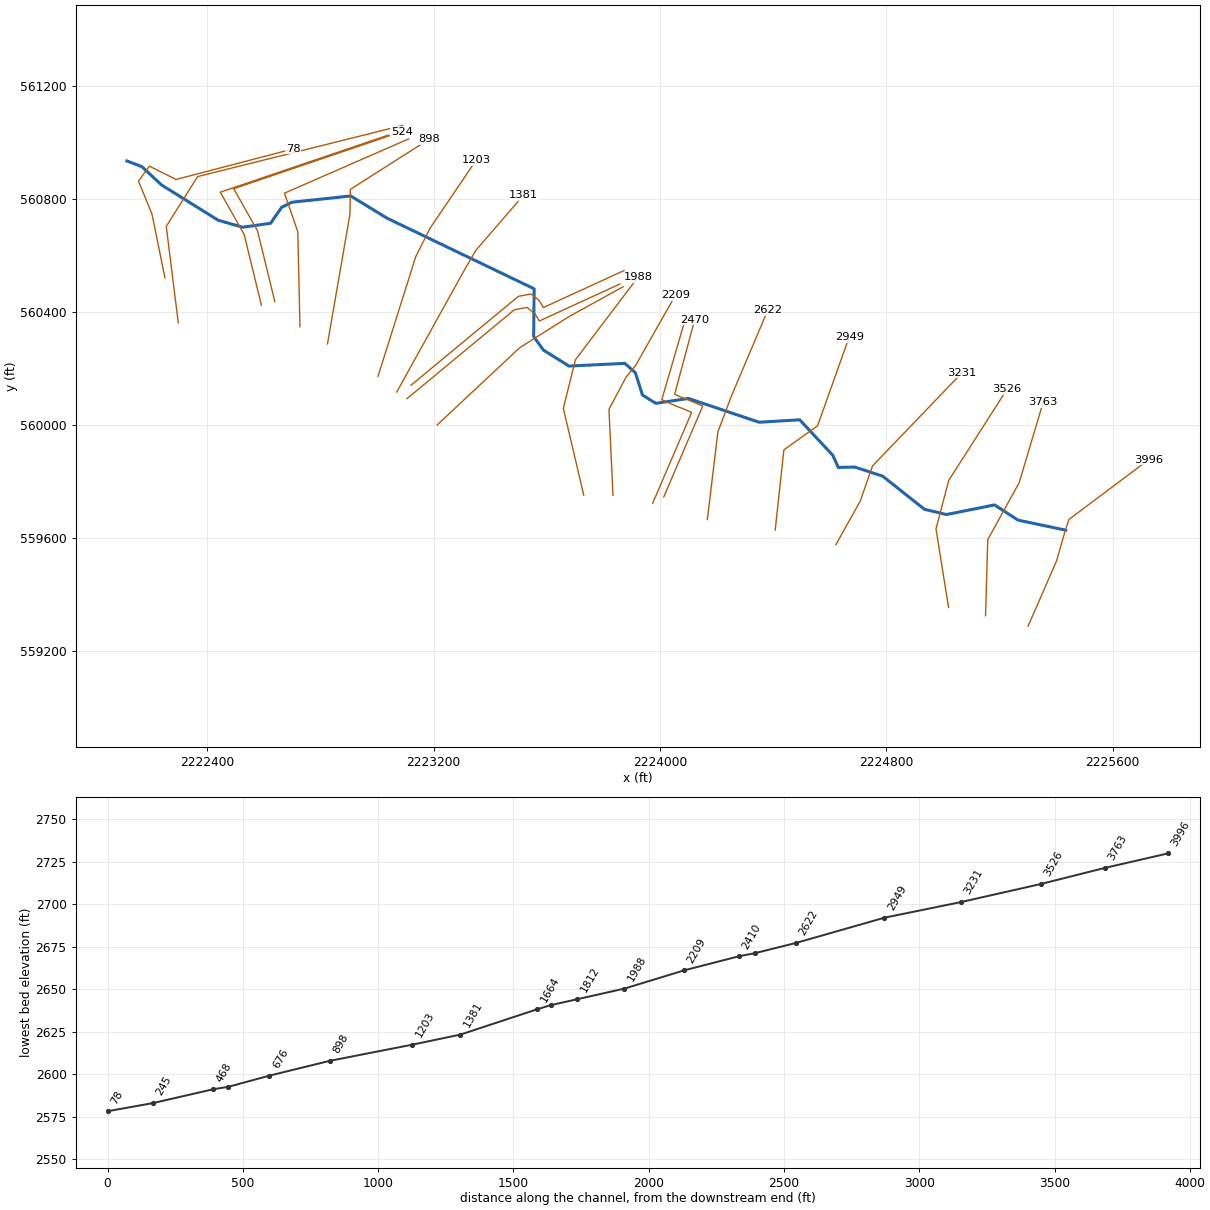
--- VALLEYFK1.prj (project) ---

Proj Title=VALLEYFK1
Current Plan=p01
Default Exp/Contr=0,0
English Units
Geom File=g01
Flow File=f01
Plan File=p01
BEGIN DESCRIPTION:
----------MODEL BY WOOD PLC 2022----------
AFH study
Randolph County, WV
HEC-RAS Version: RAS 6.2
Vertical Datum: NAVD88
Projection: NAD 1983 StatePlane West Virginia S FIPS 4702 (US Feet)
Terrain: 1-meter LIDAR (FEMA Region III 3DEP collected 2016-2018)
Land Use: 2019 NLCD
Hydrologic Method:
WV SIR2010-5033 regression equations
Additional Model Notes:
VALLEYFK Upper Reach
Split VALLEYFK at the confluence with MUDLKRN
END DESCRIPTION:
DSS Export Rating Curves= 0
DSS Export Rating Curve Sorted= 0
DSS Export Volume Flow Curves= 0
DXF OffsetX= 0
DXF OffsetY= 0
DXF ScaleX= 0
DXF ScaleY= 0

--- VALLEYFK1.p01 (plan) ---

Plan Title=Floodplain
Program Version=6.20
Short Identifier=Floodplain
Geom File=g01
Flow File=f01
Subcritical Flow
K Sum by GR= 0
Std Step Tol= 0.01
Critical Tol= 0.01
Num of Std Step Trials= 20
Max Error Tol= 0.3
Flow Tol Ratio= 0.001
Split Flow NTrial= 30
Split Flow Tol= 0.02
Split Flow Ratio= 0.02
Log Output Level= 0
Friction Slope Method= 1
Unsteady Friction Slope Method= 2
Unsteady Bridges Friction Slope Method= 1
Parabolic Critical Depth
Global Vel Dist= 0 , 0 , 0
Global Log Level= 0
CheckData=True
Encroach Param=-1 ,0,0, 0
Mapping Interval=1HOUR
Computation Time Step Use Courant=        0
Computation Time Step Use Time Series=    0
Computation Time Step Count To Double=0
Computation Time Step Max Doubling=0
Computation Time Step Max Halving=0
Computation Time Step Residence Courant=0
Run HTab= 0
Run UNet= 0
Run Sediment= 0
Run PostProcess= 0
Run WQNet= 0
Run RASMapper=-1
UNET Theta= 0
UNET Theta Warmup= 0
UNET ZTol= 0
UNET ZSATol= 0
UNET MxIter= 0
UNET Max Iter WO Improvement= 0
UNET MaxInSteps= 0
UNET DtIC= 0
UNET DtMin= 0
UNET MaxCRTS= 0
UNET WFStab= 0
UNET SFStab= 0
UNET WFX= 1
UNET SFX= 1
UNET Gravity=32.174
UNET 1D Methodology=Finite Difference
UNET DSS MLevel= 1
UNET Pardiso=0
UNET DZMax Abort= 0
UNET Use Existing IB Tables= 0
UNET Froude Reduction=False
UNET Froude Limit= 0
UNET Froude Power= 0
UNET D1 Cores= 0
UNET WindReference=Eulerian
UNET WindDragFormulation=Hsu (1988)
UNET D2 Coriolis=0
UNET D2 Cores= 0
UNET D2 Theta= 1
UNET D2 Theta Warmup= 1
UNET D2 Z Tol= 0.01
UNET D2 Volume Tol= 0.01
UNET D2 Max Iterations= 20
UNET D2 Equation= 0
UNET D2 RampUpFraction=0.1
UNET D2 TimeSlices= 1
UNET D2 Turbulence Formulation=Non-Conservative (original)
UNET D2 Eddy Viscosity=0.3
UNET D2 Transverse Eddy Viscosity=0.1
UNET D2 Smagorinsky Mixing=0
UNET D2 BCVolumeCheck=0
UNET D2 Cores=0
UNET D2 SolverType=PARDISO (Direct)
UNET D2 Minimum Iterations= 2147483647
UNET D2 Maximum Iterations= 2147483647
UNET D2 Restart Number= 10
UNET D2 Relaxation Coeff=1.3
UNET D2 SOR Precondition Iterations= 10
UNET D2 ILUT Maximum Fill= 8
UNET D2 ILUT Tolerance=1E-08
UNET D1D2 MaxIter= 0
UNET D1D2 ZTol=0.01
UNET D1D2 QTol=0.1
UNET D1D2 MinQTol=1
Write IC File= 0
Write IC File at Fixed DateTime=0
Write IC File at Sim End=0
Echo Input=False
Echo Parameters=False
Echo Output=False
Write Detailed= 0
HDF Write Warmup=0
HDF Write Time Slices=0
HDF Flush=0
HDF Compression= 1
HDF Chunk Size= 1
HDF Spatial Parts= 1
HDF Use Max Rows=0
HDF Fixed Rows= 1
Calibration Method= 0
Calibration Iterations= 20
Calibration Max Change=0.05
Calibration Tolerance=0.2
Calibration Maximum=1.5
Calibration Minimum=0.5
Calibration Optimization Method= 1
WQ AD Non Conservative
WQ ULTIMATE=-1
WQ Max Comp Step=1HOUR
WQ Output Interval=15MIN
WQ Output Selected Increments= 0
WQ Output face flow=0
WQ Output face velocity=0
WQ Output face area=0
WQ Output face dispersion=0
WQ Output cell volume=0
WQ Output cell surface area=0
WQ Output cell continuity=0
WQ Output cumulative cell continuity=0
WQ Output face conc=0
WQ Output face dconc_dx=0
WQ Output face courant=0
WQ Output face peclet=0
WQ Output face adv mass=0
WQ Output face disp mass=0
WQ Output cell mass=0
WQ Output cell source sink temp=0
WQ Output nsm pathways=0
WQ Output nsm derived pathways=0
WQ Create Restart=0
WQ Fixed Restart=0
WQ System Summary=0
WQ Write To DSS=0
Sorting and Armoring Iterations= 10
XS Update Threshold= 0.02
Bed Roughness Predictor= 0
Hydraulics Update Threshold= 0.02
Energy Slope Method= 1
Volume Change Method= 1
Sediment Retention Method= 0
Sediment TS Multiplier= 1
Warm Up Method= 0
XS Weighting Method= 0
Number of US Weighted Cross Sections= 1
Number of DS Weighted Cross Sections= 1
Upstream XS Weight=0
Main XS Weight=1
Downstream XS Weight=0
Number of DS XS's Weighted with US Boundary= 1
Upstream Boundary Weight= 1
Weight of XSs Associated with US Boundary= 0
Number of US XS's Weighted with DS Boundary= 1
Downstream Boundary Weight= 0.5
Weight of XSs Associated with DS Boundary= 0.5
Percentile Method= 0
Sediment Output Level= 3
Mass or Volume Output= 0
Output Increment Type= 1
Profile and TS Output Increment= 1
Transport Output Increment 1
XS Output Flag= 0
XS Output Increment= 10
Read HDF5 Sediment Hotstart= 0
Sediment Hotstart Type= 0
Write Gradation File= 0
Read Gradation Hotstart= 0
Write HDF5 File= 1
Write Binary Output= 1
Write DSS Sediment File= 0
DSS Sediment Output Type= 1
SV Curve= 0
Specific Gage Flag= 0
Subcell Erosion Methods= 0
Subcell Deposition Methods= 0
Advection Scheme= 1
Matrix Solver= 0
Implicit Weighting Factor= 1
Maximum Outer Loop Convergence Iterations= 5
Convergence Maximum Absolute= 0.001
Convergence RMSE= 0.0001
Grain Fractions Max Abs Error= 0.001
Max Subgrid Regions= 1
Max Subgrid Length Scale= 3.402823E+38
Initial Layer Thickness= 3.402823E+38
Min Layer Thickness= 3.402823E+38
Max Layer Thickness= 3.402823E+38
Number of Layers= 5

--- VALLEYFK1.f01 (steady flow) ---

Flow Title=Flow
Program Version=6.20
Number of Profiles= 1
Profile Names=P100yr
River Rch & RM=VALLEYFK1,Main,3996
     508
River Rch & RM=VALLEYFK1,Main,245
     971
Boundary for River Rch & Prof#=VALLEYFK1,Main            , 1
Up Type= 0
Dn Type= 3
Dn Slope=0.02868
DSS Import GetInterval= 0
DSS Import GetPeak= 0
DSS Import FillOption= 0

--- VALLEYFK1.g01 (geometry) ---

Geom Title=Geometry
Program Version=6.20

River Reach=VALLEYFK1       ,Main
Reach XY= 30
     2225433.605      559627.211     2225265.045      559662.789
     2225181.869      559716.621     2225012.484      559682.449
     2224934.474      559700.996     2224786.904      559818.184
     2224688.766      559850.446     2224629.786      559849.434
     2224610.689      559891.968     2224493.501      560017.836
     2224350.179      560009.156     2224100.272      560093.357
     2223984.821      560075.996     2223937.946       560105.51
     2223912.772      560184.503     2223875.446      560217.489
     2223678.397       560207.94     2223588.119      560264.364
     2223553.397      560312.107     2223555.133      560481.378
     2223035.168      560731.378     2222906.913      560809.937
     2222699.003      560787.749     2222662.772      560769.789
     2222623.781      560713.235     2222524.968       560699.26
     2222438.163      560724.217     2222238.833      560848.588
      2222168.61      560913.757     2222115.939      560933.764

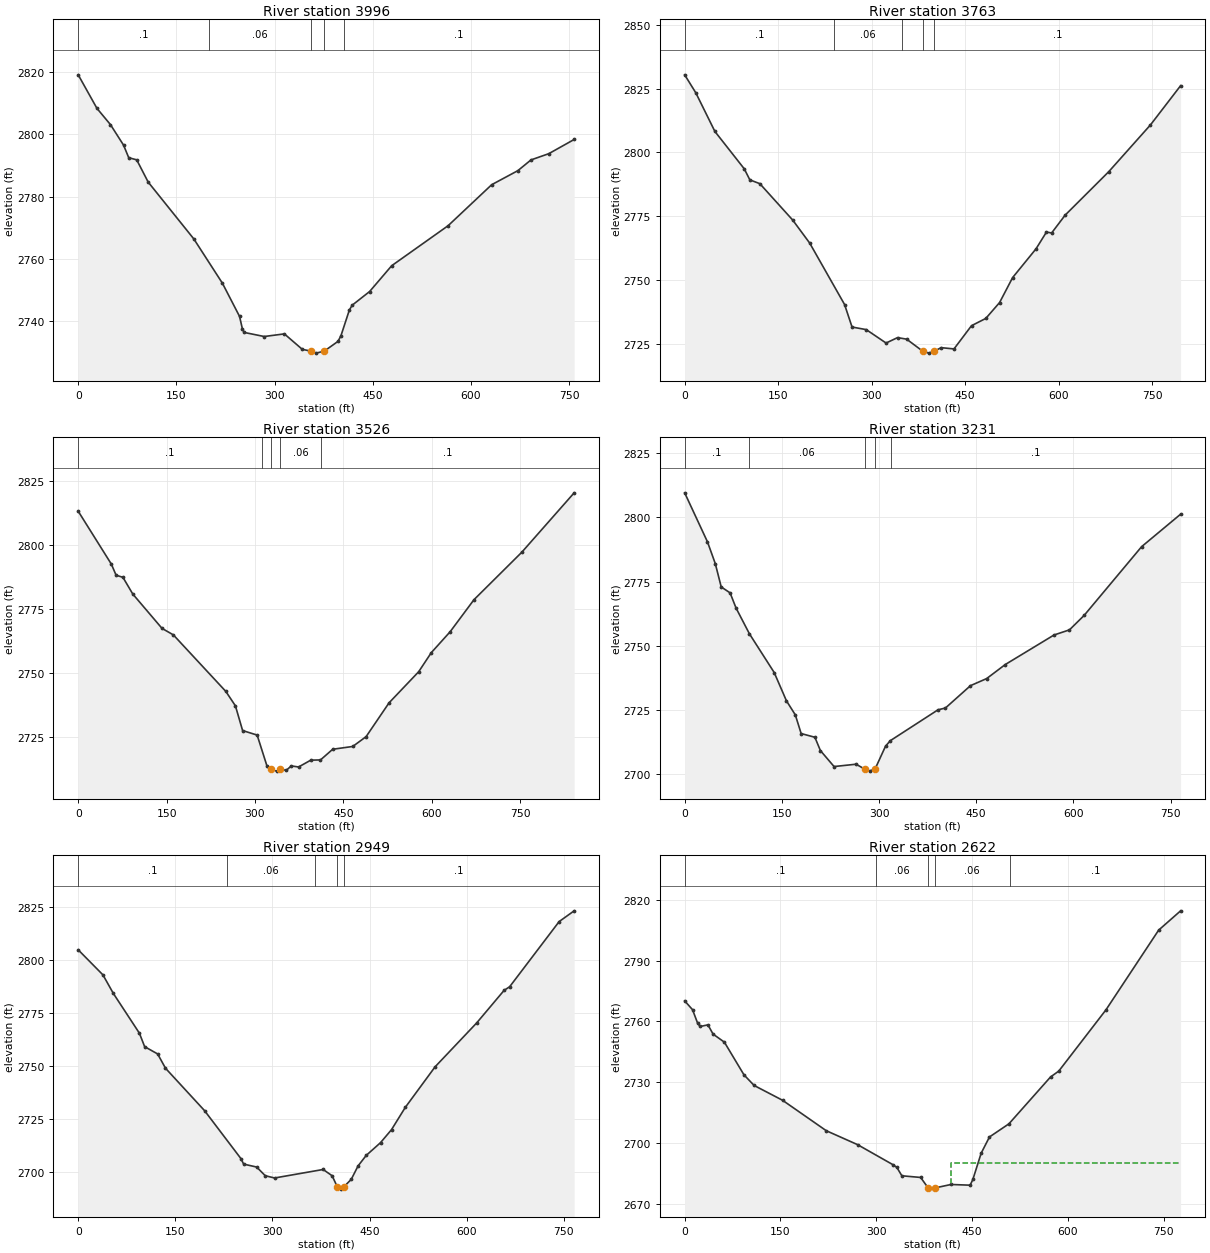
Type RM Length L Ch R = 1 ,3996    ,235.4,233.6,232
XS GIS Cut Line= 5
 2225300.4837644559287.2337226412225401.21544113559518.182381021
2225432.42681091559627.3912343222225445.24550237559665.374880999
2225726.88561977559876.829550728
#Sta/Elev= 30
       0 2818.96    28.6 2808.23    49.3 2803.01    69.3 2796.44    77.2 2792.42
    89.4 2791.74   106.9 2784.62   176.7  2766.4   220.3 2752.25   246.5 2741.62
   250.9 2737.61   253.5 2736.48   284.2 2735.17     315 2736.01   342.4 2731.06
   355.72730.488   363.5 2729.85  375.952730.487     397 2733.62   401.5 2735.44
   414.3 2743.64   418.6 2745.19   445.3 2749.58     479 2757.84   565.2 2770.65
   631.8 2783.78   671.8 2788.28   691.8 2791.71     719 2793.71   757.8 2798.26
#Mann= 5 ,-1,0
       0      .1       0     200     .06       0   355.7    .045       0
  375.95     .06       0  405.54      .1       0
Bank Sta=355.7,375.95
XS Rating Curve= 0 ,0
Exp/Cntr=0.3,0.1

Type RM Length L Ch R = 1 ,3763    ,234,237.3,239.5
XS GIS Cut Line= 4
2225150.29639712559324.6729827092225158.20855659559593.769953796
2225269.34404714559795.6199903982225353.81919268560079.609822093
#Sta/Elev= 30
       0 2830.44    17.9 2823.37    48.5 2808.23    95.6 2793.58   104.6 2789.24
   120.6 2787.76   173.4 2773.47   200.6 2764.47   256.6 2740.36   268.6 2731.53
   291.4 2730.52   323.2 2725.26   341.6 2727.38   356.2 2726.78  382.352722.003
   391.8  2721.3  399.972722.004   411.6 2723.44   432.2 2722.95   460.3 2732.06
   483.2  2734.9   505.4 2741.14   526.3 2750.93   563.9 2762.22   580.6 2768.78
   588.9 2768.42   610.6 2775.42   680.7 2792.49   747.5  2810.8   795.9 2826.19
#Mann= 5 ,-1,0
       0      .1       0     240     .06       0  349.21      .1       0
  382.35    .045       0  399.97      .1       0
Bank Sta=382.35,399.97
XS Rating Curve= 0 ,0
Exp/Cntr(USF)=0,0
Exp/Cntr=0.3,0.1

Type RM Length L Ch R = 1 ,3526    ,294.2,294.4,293.6
XS GIS Cut Line= 4
2225019.58512133559353.706670858 2224975.1779494559631.920919929
2225020.23867708559803.3716489832225226.23208127560125.941738412
#Sta/Elev= 30
       0 2813.21    56.2 2792.59    64.3 2788.25    75.9 2787.42    92.6 2780.91
   142.2 2767.51   161.5 2764.96   250.6 2742.89   266.8 2737.28     279 2727.64
   303.7 2725.87   320.3 2713.86  327.55 2712.47   336.8 2711.81   342.5 2712.48
   353.3 2712.15   361.6 2713.84     374 2713.43   394.7 2716.09   411.2 2716.18
   431.9 2720.34   465.9 2721.43   488.6 2725.26   527.6 2738.47   577.8 2750.58
   599.3 2758.05   631.2 2766.18   671.7  2778.7   752.8  2797.2   841.7 2820.39
#Mann= 5 ,-1,0
       0      .1       0  311.74     .06       0  327.55    .045       0
   342.5     .06       0  411.74      .1       0
Bank Sta=327.55,342.5
XS Rating Curve= 0 ,0
Exp/Cntr=0.3,0.1

Type RM Length L Ch R = 1 ,3231    ,285.6,282.7,277.8
XS GIS Cut Line= 4
2224621.59128807559575.873479604 2224707.7481136559730.804613241
2224750.98769873559854.5679308112225067.41999543560184.637908165
#Sta/Elev= 30
       0 2809.51    35.2 2790.42    47.3 2781.93    56.4 2772.89    70.1 2770.58
    79.3 2764.68    99.9 2754.67   138.2 2739.58   157.1 2728.57   170.8  2723.1
   179.8 2715.83     201 2714.39   209.5 2709.22   230.6 2702.99   264.5  2703.9
  277.742702.042   285.7 2701.21  293.942702.042   310.1 2710.94   317.5 2713.07
     391 2725.06   402.6 2725.78   441.2 2734.47   466.2 2737.23   494.9 2742.69
   570.2 2754.19     594 2756.18   616.6 2761.79   705.4 2788.56   765.6  2801.2
#Mann= 5 ,-1,0
       0      .1       0     100     .06       0  277.74    .045       0
  293.94     .06       0  318.37      .1       0
Bank Sta=277.74,293.94
XS Rating Curve= 0 ,0
Exp/Cntr(USF)=0,0
Exp/Cntr=0.3,0.1

Type RM Length L Ch R = 1 ,2949    ,323.8,327,329.7
XS GIS Cut Line= 4
2224406.90737726559627.1987835312224437.67379207559911.365505256
2224556.79028172 559996.572413222224668.50339147560311.055701061
#Sta/Elev= 30
       0 2804.79    38.2 2792.98    54.3 2784.22    94.5 2765.51   102.6 2759.16
   122.7 2755.72   134.8    2749   195.1 2729.02   251.4 2706.37   255.5 2703.81
   275.6 2702.43   288.9 2698.34   303.3 2697.27   378.3 2701.28   392.2 2698.32
  400.192693.078   405.8 2692.02  410.192693.077   421.7 2696.62   432.3 2702.98
   444.8  2707.9   466.9 2713.91   483.9 2720.04   505.1  2730.5   551.3 2749.69
   615.5 2770.36   657.8 2785.69   666.4  2787.4   742.8  2818.1     766 2823.17
#Mann= 5 ,-1,0
       0      .1       0     230     .06       0  365.83      .1       0
  400.19    .045       0  410.19      .1       0
Bank Sta=400.19,410.19
XS Rating Curve= 0 ,0
Exp/Cntr=0.3,0.1

Type RM Length L Ch R = 1 ,2622    ,143.2,151.3,158.4
BEGIN DESCRIPTION:
structure xs 4
END DESCRIPTION:
XS GIS Cut Line= 4
2224167.17356894559664.9939667842224204.49513079559974.970272168
2224252.89256518560103.431246382 2224380.4225439 560404.84956054
#Sta/Elev= 30
       0 2770.14    12.3 2765.79    20.3  2759.1    24.4 2757.49    36.4 2758.31
    44.5 2753.73    62.2 2749.74    92.9  2733.6   108.8 2728.36   153.3 2721.05
   221.8 2706.01   270.8 2699.13   326.1 2689.25   332.3 2687.89   340.2 2683.75
   369.6 2682.93   381.4 2677.73     383 2677.16   391.5 2677.72   417.2 2679.45
   447.1 2679.11   451.4 2681.94   464.4 2694.91   477.4 2702.93   507.9 2709.42
     573 2732.54     586 2735.48   659.9 2765.73   742.4 2805.09   776.8 2814.62
#Mann= 5 ,-1,0
       0      .1       0     300     .06       0   381.4    .045       0
   391.5     .06       0  509.49      .1       0
#XS Ineff= 2 , 0
                          417.32         2690.19
Permanent Ineff=
       F       F
Bank Sta=381.4,391.5
XS Rating Curve= 0 ,0
Exp/Cntr(USF)=0,0
Exp/Cntr=0.3,0.1

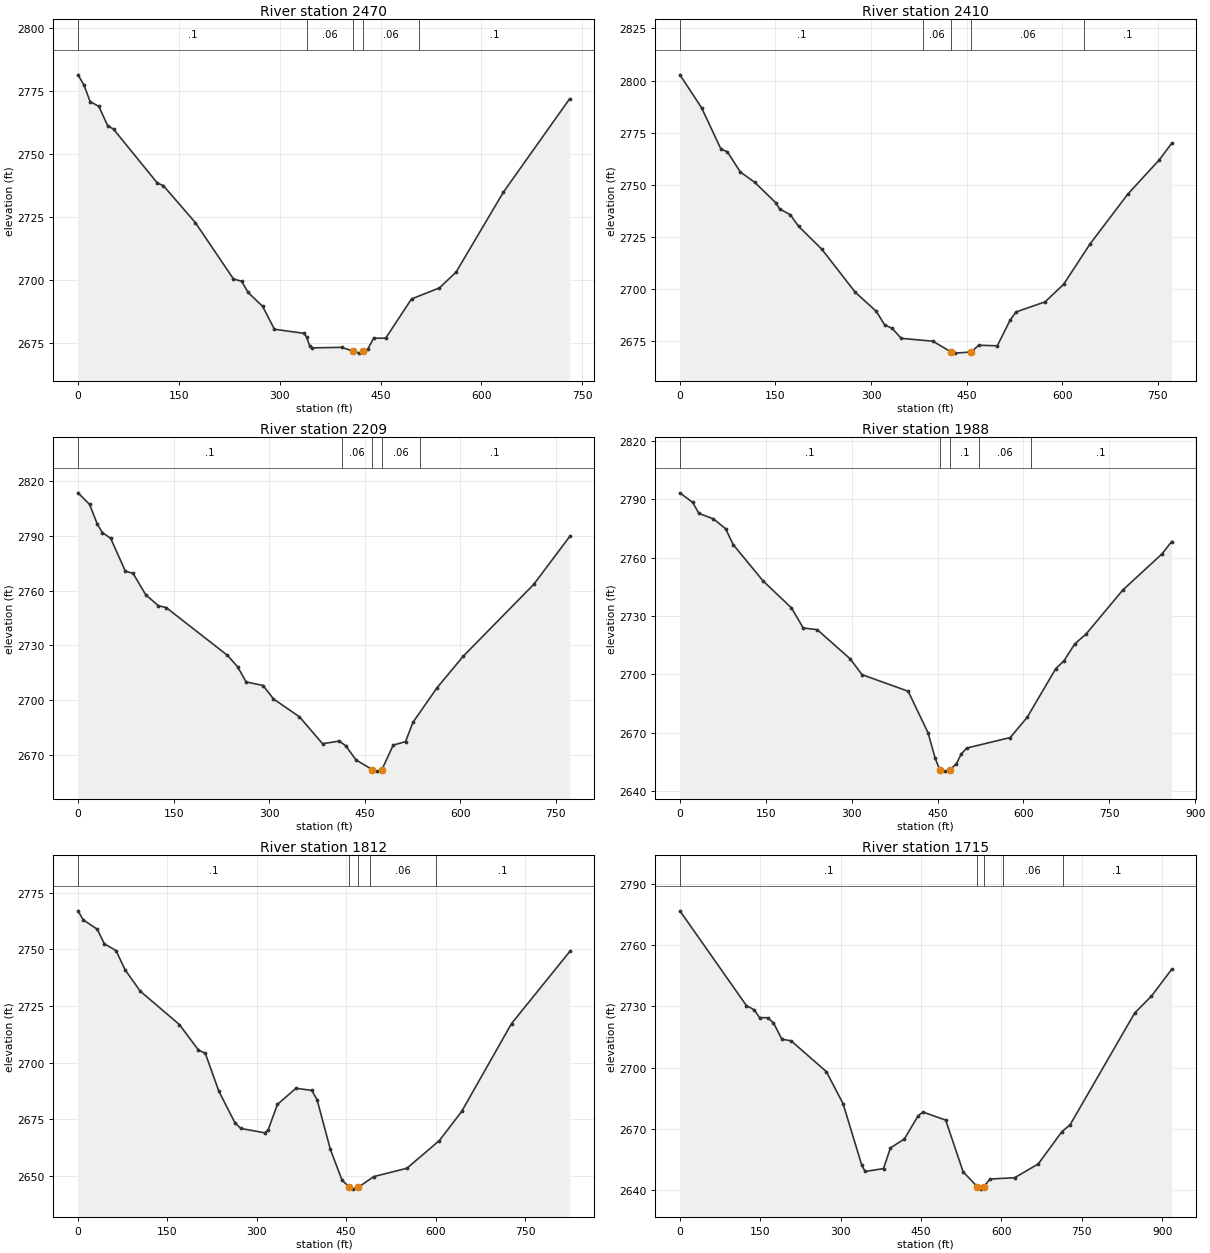
Type RM Length L Ch R = 1 ,2470    ,56.2,60.8,70.5
BEGIN DESCRIPTION:
structure xs 3
END DESCRIPTION:
XS GIS Cut Line= 6
2224013.07008425559744.6232618112224150.90493221560066.416565541
2224119.44451202560080.1316546992224070.23801714560099.706094833
2224051.69338578560108.1424506162224122.60281338560372.534690145
#Sta/Elev= 30
       0 2781.28     8.9 2777.21      18 2770.72    31.1 2768.77    44.1 2761.14
    52.8  2759.8   118.1 2738.43   126.8 2737.49   174.7 2722.76   231.2 2700.52
   243.5 2699.57     253 2695.17   274.7 2689.65   292.2 2680.61   335.7 2679.02
     340 2677.59   344.4 2674.14   348.7 2673.25   392.2 2673.46   409.6 2671.92
   418.5 2671.17  423.34 2671.91   430.9 2672.67   439.6 2677.05   457.7  2677.1
   496.1 2692.62   537.5 2696.96   562.3  2703.2   632.7 2734.84   731.5 2771.89
#Mann= 5 ,-1,0
       0      .1       0     340     .06       0   409.6    .045       0
  423.34     .06       0  507.72      .1       0
Bank Sta=409.6,423.34
XS Rating Curve= 0 ,0
Exp/Cntr=0.3,0.1

Type RM Length L Ch R = 1 ,2410    ,217.3,200.8,175.7
BEGIN DESCRIPTION:
structure xs 2
END DESCRIPTION:
XS GIS Cut Line= 6
2223973.81679534559721.906686599 2224111.6516433560043.699990329
2224080.19122311560057.4150794872224056.10218352560066.509747968
  2224006.330523560089.1595038842224092.11717867 560384.05990176
#Sta/Elev= 30
       0 2802.75      34 2786.97    64.5 2767.08    74.4 2765.89    94.9 2756.16
   117.7 2751.13   150.5  2741.4   156.6  2738.4   173.3 2735.66   186.3 2730.08
   222.5 2719.22   275.4 2698.42   308.2 2689.36   321.2  2682.9   333.3 2681.11
   347.3 2676.38   397.2 2674.99     4252669.946     432 2669.28   457.12669.835
     469 2673.08   498.2 2672.79     518 2684.95   527.6 2689.04   573.2 2693.87
   602.3  2702.3     644 2721.74     703 2745.53   752.3 2761.93   771.9  2769.9
#Mann= 5 ,-1,0
       0      .1       0  380.97     .06       0     425    .045       0
   457.1     .06       0  634.82      .1       0
Bank Sta=425,457.1
XS Rating Curve= 0 ,0
Exp/Cntr=0.3,0.1

Type RM Length L Ch R = 1 ,2209    ,220.6,221,226.1
BEGIN DESCRIPTION:
structure xs 1
END DESCRIPTION:
XS GIS Cut Line= 5
 2223833.6659674559750.9835456922223819.58256806560054.747770773
2223880.36258772560169.5730314322223913.96110687560210.447887972
2224054.14885695 560458.40035775
#Sta/Elev= 30
       0 2813.78    18.2 2807.41    30.2 2796.68    38.2 2791.93    51.1 2788.92
    74.3 2770.79    86.3 2769.63   106.3 2757.83   126.3 2751.79   138.3 2750.84
   234.4 2724.63   250.5 2718.31   263.8 2710.02   290.5 2708.04   306.8 2700.67
   347.6 2690.84   383.8 2676.09   409.9 2677.55     420 2675.04   436.4 2667.17
  462.112661.842   469.7 2661.05   476.92661.843   494.7 2675.35     514 2677.23
   525.8 2687.92   563.6 2706.88   604.9 2724.22   715.2 2763.53   771.8 2789.88
#Mann= 5 ,-1,0
       0      .1       0  414.09     .06       0  462.11    .045       0
   476.9     .06       0  536.92      .1       0
Bank Sta=462.11,476.9
XS Rating Curve= 0 ,0
Exp/Cntr(USF)=0,0
Exp/Cntr=0.3,0.1

Type RM Length L Ch R = 1 ,1988    ,182.5,175.4,170.2
XS GIS Cut Line= 5
2223730.36850656559751.5048029862223658.27187552560058.617154683
2223689.05795375560182.1615049782223701.23004525560230.427911323
2223922.29599657560522.626104755
#Sta/Elev= 30
       0 2793.24    22.3 2788.33    33.2 2782.67    58.4 2779.89    79.8 2774.83
    93.1 2766.65   145.5 2747.92   194.8 2734.19   215.4 2723.84     240 2722.95
   297.5 2707.95   318.1 2699.87   398.7 2691.34   433.5 2669.97   445.9 2656.91
  453.81 2651.04   462.4 2650.32  471.382651.042     483 2654.06   491.3 2659.09
     501 2662.17     577 2667.57   606.4 2677.88   656.5 2702.94   670.8 2706.97
   689.7 2715.65   709.6 2720.76   773.6 2743.33   842.2 2761.91     859 2768.24
#Mann= 5 ,-1,0
       0      .1       0  453.81    .045       0  471.38      .1       0
  522.56     .06       0  612.56      .1       0
Bank Sta=453.81,471.38
XS Rating Curve= 0 ,0
Exp/Cntr=0.3,0.1

Type RM Length L Ch R = 1 ,1812    ,106.3,97.5,90.8
BEGIN DESCRIPTION:
structure xs 4
END DESCRIPTION:
XS GIS Cut Line= 4
2223211.98313723559999.1655535922223503.82896235560272.614254913
2223678.20142935560383.0324991792223869.83611984560488.662329758
#Sta/Elev= 30
       0 2767.09     8.8 2763.07    32.2 2758.98    44.1 2752.54    63.8  2749.5
      79 2741.01   104.4 2731.57   170.2 2716.78   201.9 2705.59   213.6 2704.04
   236.4 2687.28   263.4 2673.33   273.2 2670.85     313 2668.95   318.9 2670.18
   334.6 2681.51   365.7 2688.62   392.1  2687.7     401 2683.66   423.4  2661.6
     443 2647.99   455.52644.863   461.9 2644.03  470.42 2644.88   496.3 2649.58
   551.8 2653.26   606.4 2665.53   643.9 2678.48   727.3 2717.22   825.1 2749.13
#Mann= 5 ,-1,0
       0      .1       0   455.5    .045       0  470.42      .1       0
  489.94     .06       0  599.94      .1       0
Bank Sta=455.5,470.42
XS Rating Curve= 0 ,0
Exp/Cntr(USF)=0,0
Exp/Cntr=0.3,0.1

Type RM Length L Ch R = 1 ,1715    ,51,50.6,50.3
BEGIN DESCRIPTION:
structure xs 2
END DESCRIPTION:
XS GIS Cut Line= 6
2223105.80844748560092.6433028812223485.05640936560407.166754002
2223530.06432929560415.4549500012223557.48305906560393.503324366
2223573.63692915560367.5350708392223858.38680741560498.403675498
#Sta/Elev= 30
       0 2776.77   124.2 2730.36   138.7 2728.36   148.6 2724.49   163.8 2724.46
   174.6 2721.95   190.2 2713.96   207.6 2713.13   273.3 2698.06   304.5 2682.35
   339.2 2652.38   345.5 2649.19   379.9 2650.61   392.8  2660.7   418.8 2665.12
   444.8 2676.57   453.7 2678.27   495.9 2674.34   528.4 2649.08   554.9 2641.73
   561.7 2640.56   566.8 2641.75   578.7  2645.5   624.6 2646.15   668.6 2652.87
   712.9 2668.72     728 2672.04   848.6 2726.78   879.9 2735.03   917.6 2748.17
#Mann= 5 ,-1,0
       0      .1       0   554.9    .045       0   566.8      .1       0
  603.59     .06       0  714.17      .1       0
Bank Sta=554.9,566.8
XS Rating Curve= 0 ,0
Exp/Cntr(USF)=0,0
Exp/Cntr=0.3,0.1

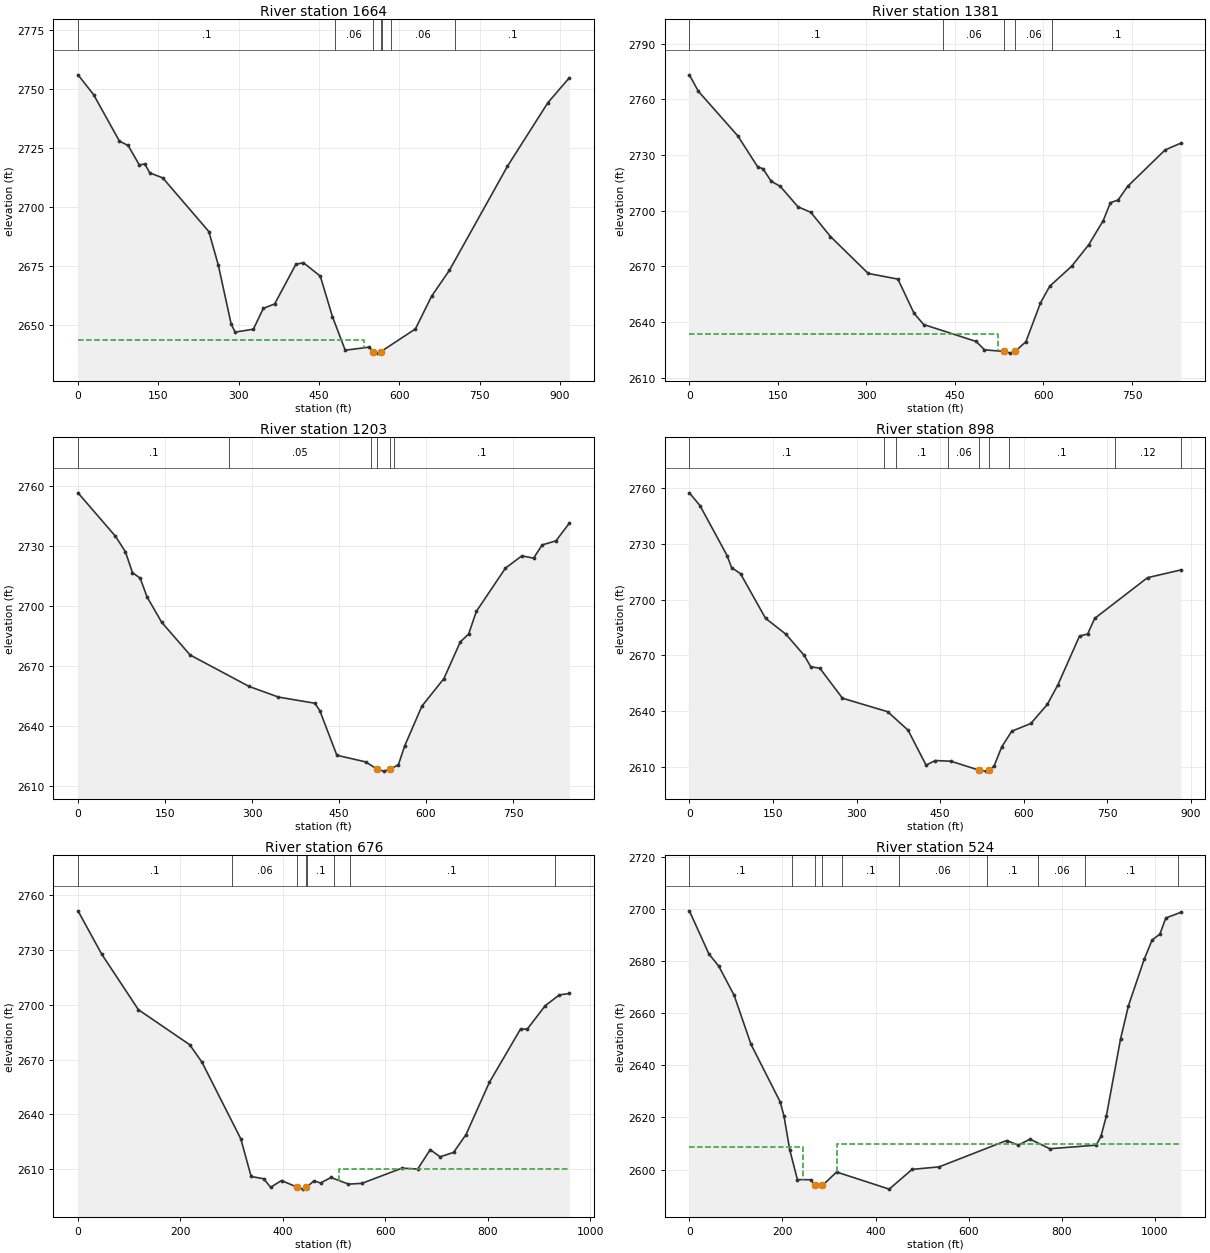
Type RM Length L Ch R = 1 ,1664    ,268.2,283.1,290.5
BEGIN DESCRIPTION:
structure xs 2
END DESCRIPTION:
XS GIS Cut Line= 6
2223120.14352963560140.2116440882223499.39149151560454.735095209
2223544.39941144560463.0232912082223571.81814121560441.071665572
 2223587.9720113560415.1034120462223872.72188956560545.972016705
#Sta/Elev= 30
       0 2756.18    29.1  2747.8    77.4 2728.03    93.6  2726.2   114.4 2717.99
   124.8 2718.31   134.2 2714.55   158.2 2712.46   244.3 2689.68   262.1 2675.33
   285.9 2650.52   293.3 2647.01   327.4 2648.23   346.1 2657.09   367.2 2658.97
   406.9 2675.82     421 2676.43   452.4 2670.75   475.1 2653.55   498.9 2639.33
   543.3 2640.62   551.72638.725   558.7 2638.09  565.61 2638.74     630 2648.36
   660.2 2662.24   693.4 2673.22   801.9 2717.42   877.3 2744.35   917.6 2755.01
#Mann= 7 ,-1,0
       0      .1       0     480     .06       0   551.7    .045       0
  565.61     .06       0  568.47      .1       0  583.59     .06       0
  704.17      .1       0
#XS Ineff= 2 , 0
          533.42 2643.51
Permanent Ineff=
       F       F
Bank Sta=551.7,565.61
XS Rating Curve= 0 ,0
Exp/Cntr(USF)=0,0
Exp/Cntr=0.3,0.1

Type RM Length L Ch R = 1 ,1381    ,177.2,177.8,178.5
BEGIN DESCRIPTION:
structure xs 1
END DESCRIPTION:
XS GIS Cut Line= 4
2223069.57462125 560116.002427612223314.28304513 560558.03618946
2223349.18594154560617.527595406 2223518.1248706560813.304205614
#Sta/Elev= 30
       0 2773.25    15.1 2764.43    82.2  2740.3   115.6 2723.73   124.8  2722.6
   138.5 2715.94     154 2713.12   184.2 2702.09   205.8 2699.14   239.1 2686.09
   303.1 2666.18   353.4 2663.14   380.8 2644.65   397.1 2638.64     486 2629.52
   500.1 2625.01  533.032624.152     544 2623.23  551.942624.152   570.3 2629.41
   594.9 2650.26   610.7 2659.32   647.7 2670.04   676.8 2681.71   701.3  2694.7
   713.5 2704.34   726.4 2705.74   742.8 2713.18   806.2 2732.79   832.8 2736.42
#Mann= 5 ,-1,0
       0      .1       0     430     .06       0  533.03    .045       0
  551.94     .06       0  614.22      .1       0
#XS Ineff= 2 , 0
          523.74 2633.71
Permanent Ineff=
       F       F
Bank Sta=533.03,551.94
XS Rating Curve= 0 ,0
Exp/Cntr=0.3,0.1

Type RM Length L Ch R = 1 ,1203    ,300.4,304.9,307.8
XS GIS Cut Line= 4
2223003.31948266560171.5968892142223136.88889662 560595.43871912
2223187.51126925560696.1965946232223350.21782212560936.447222828
#Sta/Elev= 30
       0 2756.48    64.6 2734.76    81.7 2727.04    93.9 2716.62   107.2 2713.78
   119.1 2704.41   144.3 2691.74   193.3 2675.39   295.2 2659.63   345.6 2654.34
   408.5 2651.25   416.9 2647.54   446.3 2625.25   496.3  2621.9  516.212618.177
   526.9 2617.31  537.752618.175   552.4 2620.51   563.2 2629.92   592.9 2649.82
   630.8 2663.58   659.1 2681.93   673.5 2685.87   686.7 2697.14   736.9 2718.82
   765.2 2724.96   785.4 2723.81   800.3 2730.43     824 2732.48   847.3 2741.39
#Mann= 6 ,-1,0
       0      .1       0     260     .05       0  504.39     .06       0
  516.21    .045       0  537.75     .06       0  544.39      .1       0
Bank Sta=516.21,537.75
XS Rating Curve= 0 ,0
Exp/Cntr(USF)=0,0
Exp/Cntr=0.3,0.1

Type RM Length L Ch R = 1 ,898     ,218.5,222.5,224.5
XS GIS Cut Line= 4
2222824.85160488560286.4471204442222904.11230541560744.683417403
2222905.60903573560833.3565885962223182.61191987 561009.76631919
#Sta/Elev= 30
       0 2757.49      19 2750.66    67.7 2723.75    75.8 2717.26    91.8    2714
   136.7 2690.01   173.3 2681.44     206 2670.09   217.9 2663.93   234.2 2663.15
   274.8 2647.02   355.9 2639.76   392.5 2629.84   424.9 2611.01   441.2 2613.49
   469.5 2613.13   520.7 2608.25   532.5  2607.8  537.32 2608.25   546.9 2610.56
   560.8 2620.91   578.6 2629.27     613 2633.44   642.4 2643.67   661.1 2653.99
   700.3 2680.46   714.8 2681.53   727.5 2689.95   822.3 2711.85   882.1 2716.01
#Mann= 9 ,-1,0
       0      .1       0     350     .05       0     370      .1       0
  465.04     .06       0   520.7    .045       0  537.32     .06       0
  573.73      .1       0  763.73     .12       0  882.13      .1       0
Bank Sta=520.7,537.32
XS Rating Curve= 0 ,0
Exp/Cntr=0.3,0.1

Type RM Length L Ch R = 1 ,676     ,147.5,151.9,151.4
BEGIN DESCRIPTION:
structure xs 4
END DESCRIPTION:
XS GIS Cut Line= 4
2222727.61883287560347.2227387052222719.84468219 560683.48536852
2222672.67180871560819.7784110352223111.64298396561011.814515452
#Sta/Elev= 30
       0 2751.56      46 2727.98     118 2697.39     218 2678.25     242 2668.69
     318 2626.62   338.1 2606.03   362.6 2604.79   376.2 2600.13   397.4 2603.81
  428.532600.114   439.7 2599.11  445.912600.114   460.9 2603.66   473.6 2602.48
   494.1  2605.5   528.1 2601.85   554.3 2602.27   632.8 2610.61   663.4 2610.12
   687.8 2620.73   707.1  2616.8   733.4 2619.23   757.7    2629   803.2 2657.54
   864.2 2686.84   877.3 2686.78   912.3 2699.58   939.9  2705.5   959.7 2706.28
#Mann= 8 ,-1,0
       0      .1       0     300     .06       0  428.53    .045       0
  445.91     .06       0  446.35      .1       0  500.58     .06       0
  530.58      .1       0  930.58     .12       0
#XS Ineff= 2 , 0
                          509.79          2610.3
Permanent Ineff=
       F       F
Bank Sta=428.53,445.91
XS Rating Curve= 0 ,0
Exp/Cntr(USF)=0,0
Exp/Cntr=0.3,0.1

Type RM Length L Ch R = 1 ,524     ,52.7,56,56.7
BEGIN DESCRIPTION:
structure xs 3
END DESCRIPTION:
XS GIS Cut Line= 4
2222638.77883912560435.6779532492222577.68631638560686.452592058
2222493.54290923560835.6270963752223086.72343813561037.600705911
#Sta/Elev= 30
       0 2699.26      42 2682.72    63.3    2678    96.1  2666.9   132.5 2648.04
     195 2626.04   203.3 2620.58   215.6 2607.67   232.1 2596.19   261.2 2596.13
   269.3 2594.01     2862593.942   316.3 2599.09   429.4 2592.53   478.6  2600.1
   536.7 2601.07   681.5 2611.17   706.8  2609.4     732  2611.7   774.4 2608.02
     874  2609.4   884.3 2612.74   896.1 2620.71   926.5 2650.15   943.4 2662.87
   977.2 2680.65   994.2 2688.04  1011.1 2690.36  1023.7 2696.52    1056 2698.69
#Mann= 10 ,-1,0
       0      .1       0     220     .06       0   269.3    .045       0
     286     .06       0  328.11      .1       0  449.38     .06       0
  639.38      .1       0  749.38     .06       0  849.38      .1       0
 1049.38     .12       0
#XS Ineff= 2 , 0
          244.31  2608.7  316.73            2610
Permanent Ineff=
       F       F
Bank Sta=269.3,286
XS Rating Curve= 0 ,0
Exp/Cntr=0.3,0.1

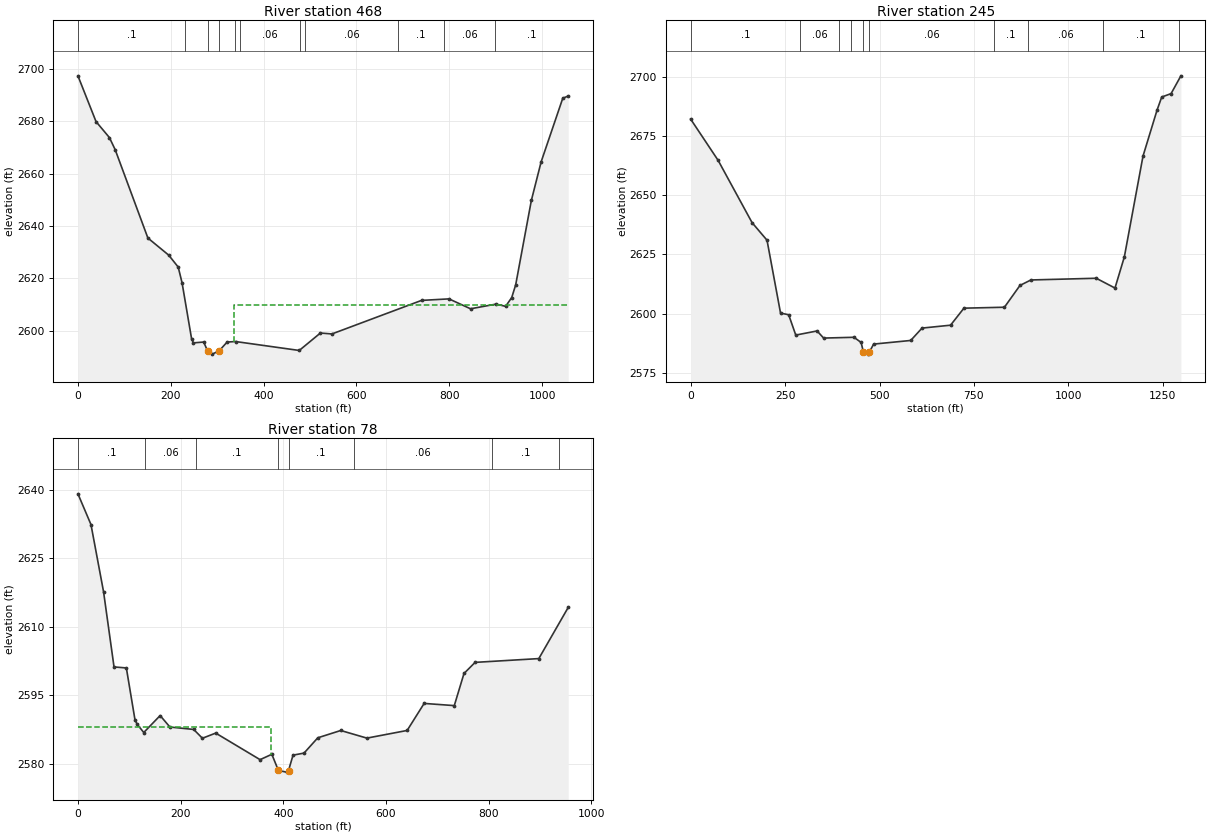
Type RM Length L Ch R = 1 ,468     ,232.7,223.2,210.3
BEGIN DESCRIPTION:
structure xs 2
END DESCRIPTION:
XS GIS Cut Line= 4
2222591.29551082 560423.290998042222530.20298808560674.065636849
2222446.05958093560823.2401411662223039.24010983561025.213750702
#Sta/Elev= 30
       0 2697.39      39 2679.91    67.8 2673.81    80.2  2669.2   150.7 2635.44
   195.4 2628.93     216 2624.35   224.3 2618.35   244.8 2596.98   248.7  2595.4
   270.9 2595.71   279.5 2592.23   289.2  2591.1     3042592.326   321.4 2595.72
   339.8  2595.9   476.7  2592.5   522.3 2599.16   547.1 2598.81   740.1 2611.62
   799.2  2612.2   845.7 2608.42   900.6  2610.2   921.2 2609.35   934.4 2612.71
   942.9 2617.55   976.7 2649.83   997.8 2664.57  1044.3 2688.81    1056 2689.68
#Mann= 11 ,-1,0
       0      .1       0     230     .06       0   279.5    .045       0
     304     .06       0  338.11      .1       0  348.11     .06       0
  479.38      .1       0  489.38     .06       0  689.38      .1       0
  789.38     .06       0  899.38      .1       0
#XS Ineff= 2 , 0
                          336.06         2609.83
Permanent Ineff=
       F       F
Bank Sta=279.5,304
XS Rating Curve= 0 ,0
Exp/Cntr=0.3,0.1

Type RM Length L Ch R = 1 ,245     ,167.8,167.2,166.6
BEGIN DESCRIPTION:
structure xs 1
END DESCRIPTION:
XS GIS Cut Line= 4
 2222297.5953047560361.0003290342222255.07393421560702.352442143
2222365.91474501560878.5047787572223089.40948571561059.370491175
#Sta/Elev= 30
       0 2682.05    72.7 2664.66   162.7 2638.37   202.2 2630.98     238 2600.25
   259.5 2599.56   278.3 2590.98   334.7 2592.72   352.1 2589.72   432.4 2590.05
   451.2 2587.89  457.482583.818   468.7 2582.95  473.152583.818   484.4 2587.18
   582.6 2588.71   612.6 2593.93   688.1 2595.15   723.5 2602.33   830.7 2602.72
   871.9 2611.92   900.8 2614.22  1073.8 2614.94  1123.4 2610.81  1148.2 2623.96
  1197.6 2666.46  1234.8 2685.85  1247.1 2691.35  1271.9 2692.79  1297.9 2700.29
#Mann= 10 ,-1,0
       0      .1       0     290     .06       0  393.99      .1       0
  423.99     .06       0  457.48    .045       0  473.15     .06       0
  802.11      .1       0  892.11     .06       0 1092.11      .1       0
 1292.11     .12       0
Bank Sta=457.48,473.15
XS Rating Curve= 0 ,0
Exp/Cntr(USF)=0,0
Exp/Cntr=0.3,0.1

Type RM Length L Ch R = 1 ,78      ,,,
XS GIS Cut Line= 6
2222250.41105489560520.276993212 2222204.6002937560745.994548934
2222156.97393733560862.6213661512222195.42666871560915.359575157
2222289.78542993560868.2936415492222703.54967706560976.504628931
#Sta/Elev= 30
       0 2639.12    25.4 2632.39    49.9 2617.67    70.3  2601.2    94.3 2600.98
   111.1 2589.63   115.2 2588.67   128.2 2586.84   160.1 2590.55   179.1 2588.04
   225.4 2587.51   242.4 2585.58   268.3 2586.71   354.7 2580.89   377.6 2582.07
390.40242578.519   406.2 2578.16410.06172578.499   418.9 2581.88   440.3 2582.33
   467.1 2585.68   511.8 2587.28   562.7 2585.61   641.1 2587.29   674.2 2593.21
   732.9 2592.73   751.8 2599.77   773.4  2602.2   897.5 2603.03   954.7 2614.23
#Mann= 8 ,-1,0
       0      .1       0     130     .06       0     230      .1       0
390.4024    .045       0410.0617      .1       0  537.01     .06       0
  807.01      .1       0  937.01     .06       0
#XS Ineff= 2 , 0
          375.23  2588.1
Permanent Ineff=
       F       F
Bank Sta=390.4024,410.0617
XS Rating Curve= 0 ,0
Exp/Cntr(USF)=0,0
Exp/Cntr=0.3,0.1
LCMann Table=0

Chan Stop Cuts=-1
Use User Specified Reach Order=0
Composite Channel Slope=5